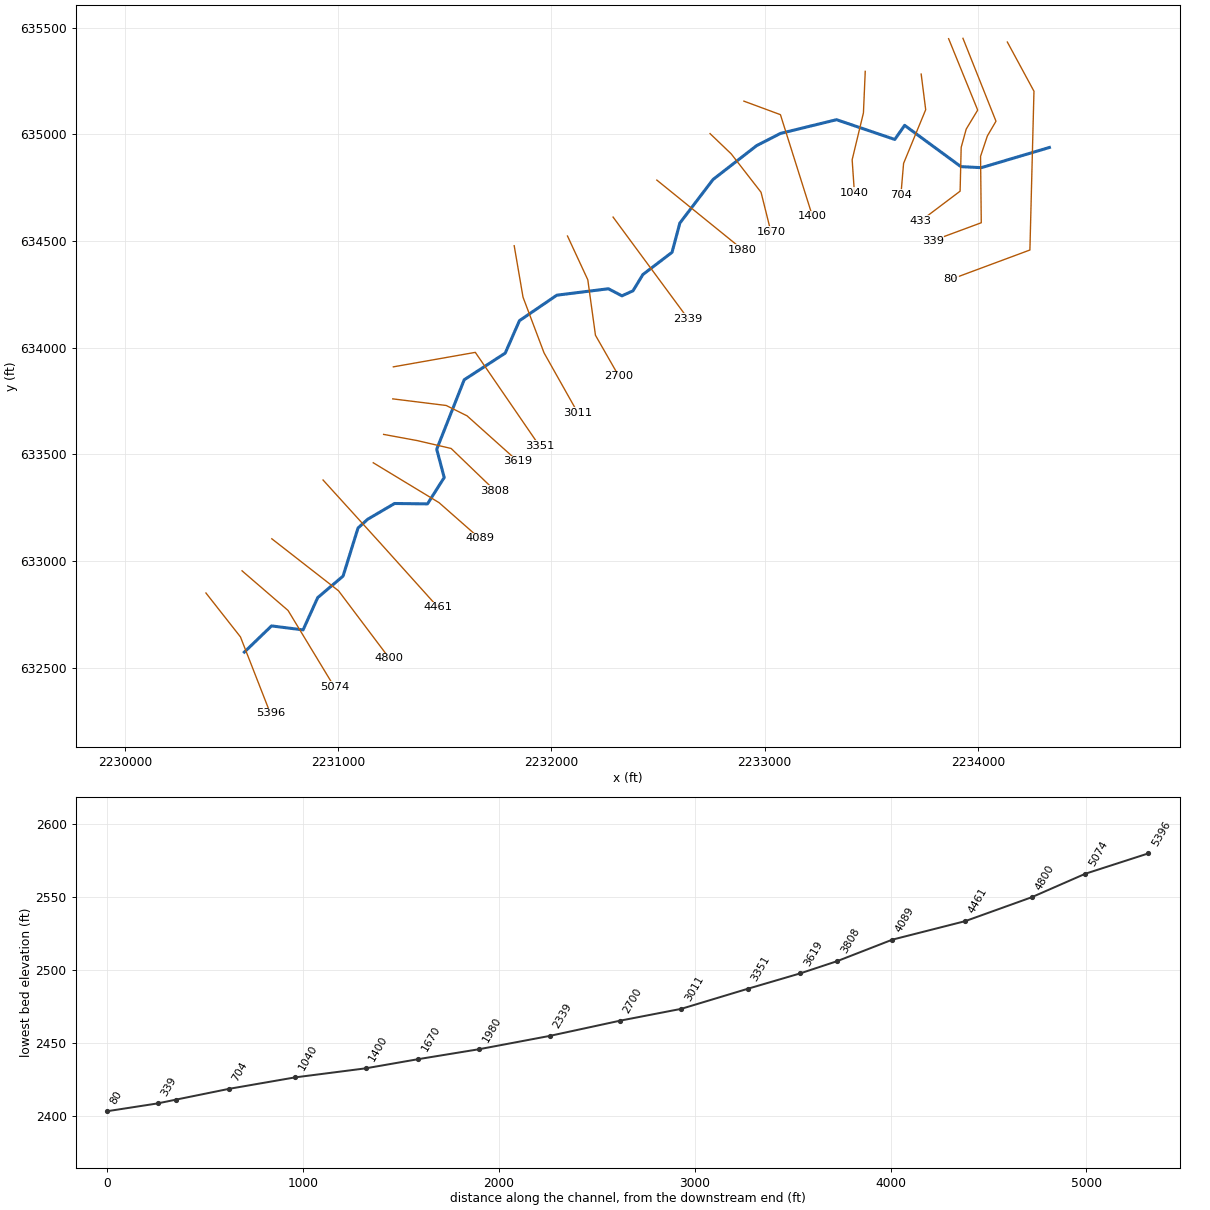
--- LIGHTRN.prj (project) ---

Proj Title=LIGHTRN
Current Plan=p01
Default Exp/Contr=0,0
English Units
Geom File=g01
Flow File=f01
Plan File=p01
BEGIN DESCRIPTION:
----------MODEL BY WOOD PLC 2022----------
AFH study
Randolph County, WV
HEC-RAS Version: RAS 6.2
Vertical Datum: NAVD88
Projection: NAD 1983 StatePlane West Virginia S FIPS 4702 (US Feet)
Terrain: 1-meter LIDAR (FEMA Region III 3DEP collected 2016-2018)
Land Use: 2019 NLCD
Hydrologic Method:
WV SIR2010-5033 regression equations
Additional Model Notes:
None
END DESCRIPTION:
DSS Export Rating Curves= 0
DSS Export Rating Curve Sorted= 0
DSS Export Volume Flow Curves= 0
DXF OffsetX= 0
DXF OffsetY= 0
DXF ScaleX= 0
DXF ScaleY= 0

--- LIGHTRN.p01 (plan) ---

Plan Title=Floodplain
Program Version=6.20
Short Identifier=Floodplain
Geom File=g01
Flow File=f01
Subcritical Flow
K Sum by GR= 0
Std Step Tol= 0.01
Critical Tol= 0.01
Num of Std Step Trials= 20
Max Error Tol= 0.3
Flow Tol Ratio= 0.001
Split Flow NTrial= 30
Split Flow Tol= 0.02
Split Flow Ratio= 0.02
Log Output Level= 0
Friction Slope Method= 1
Unsteady Friction Slope Method= 2
Unsteady Bridges Friction Slope Method= 1
Parabolic Critical Depth
Global Vel Dist= 0 , 0 , 0
Global Log Level= 0
CheckData=True
Encroach Param=-1 ,0,0, 0
Mapping Interval=1HOUR
Computation Time Step Use Courant=        0
Computation Time Step Use Time Series=    0
Computation Time Step Count To Double=0
Computation Time Step Max Doubling=0
Computation Time Step Max Halving=0
Computation Time Step Residence Courant=0
Run HTab= 0
Run UNet= 0
Run Sediment= 0
Run PostProcess= 0
Run WQNet= 0
Run RASMapper=-1
UNET Theta= 0
UNET Theta Warmup= 0
UNET ZTol= 0
UNET ZSATol= 0
UNET MxIter= 0
UNET Max Iter WO Improvement= 0
UNET MaxInSteps= 0
UNET DtIC= 0
UNET DtMin= 0
UNET MaxCRTS= 0
UNET WFStab= 0
UNET SFStab= 0
UNET WFX= 1
UNET SFX= 1
UNET Gravity=32.174
UNET 1D Methodology=Finite Difference
UNET DSS MLevel= 1
UNET Pardiso=0
UNET DZMax Abort= 0
UNET Use Existing IB Tables= 0
UNET Froude Reduction=False
UNET Froude Limit= 0
UNET Froude Power= 0
UNET D1 Cores= 0
UNET WindReference=Eulerian
UNET WindDragFormulation=Hsu (1988)
UNET D2 Coriolis=0
UNET D2 Cores= 0
UNET D2 Theta= 1
UNET D2 Theta Warmup= 1
UNET D2 Z Tol= 0.01
UNET D2 Volume Tol= 0.01
UNET D2 Max Iterations= 20
UNET D2 Equation= 0
UNET D2 RampUpFraction=0.1
UNET D2 TimeSlices= 1
UNET D2 Turbulence Formulation=Non-Conservative (original)
UNET D2 Eddy Viscosity=0.3
UNET D2 Transverse Eddy Viscosity=0.1
UNET D2 Smagorinsky Mixing=0
UNET D2 BCVolumeCheck=0
UNET D2 Cores=0
UNET D2 SolverType=PARDISO (Direct)
UNET D2 Minimum Iterations= 2147483647
UNET D2 Maximum Iterations= 2147483647
UNET D2 Restart Number= 10
UNET D2 Relaxation Coeff=1.3
UNET D2 SOR Precondition Iterations= 10
UNET D2 ILUT Maximum Fill= 8
UNET D2 ILUT Tolerance=1E-08
UNET D1D2 MaxIter= 0
UNET D1D2 ZTol=0.01
UNET D1D2 QTol=0.1
UNET D1D2 MinQTol=1
Write IC File= 0
Write IC File at Fixed DateTime=0
Write IC File at Sim End=0
Echo Input=False
Echo Parameters=False
Echo Output=False
Write Detailed= 0
HDF Write Warmup=0
HDF Write Time Slices=0
HDF Flush=0
HDF Compression= 1
HDF Chunk Size= 1
HDF Spatial Parts= 1
HDF Use Max Rows=0
HDF Fixed Rows= 1
Calibration Method= 0
Calibration Iterations= 20
Calibration Max Change=0.05
Calibration Tolerance=0.2
Calibration Maximum=1.5
Calibration Minimum=0.5
Calibration Optimization Method= 1
WQ AD Non Conservative
WQ ULTIMATE=-1
WQ Max Comp Step=1HOUR
WQ Output Interval=15MIN
WQ Output Selected Increments= 0
WQ Output face flow=0
WQ Output face velocity=0
WQ Output face area=0
WQ Output face dispersion=0
WQ Output cell volume=0
WQ Output cell surface area=0
WQ Output cell continuity=0
WQ Output cumulative cell continuity=0
WQ Output face conc=0
WQ Output face dconc_dx=0
WQ Output face courant=0
WQ Output face peclet=0
WQ Output face adv mass=0
WQ Output face disp mass=0
WQ Output cell mass=0
WQ Output cell source sink temp=0
WQ Output nsm pathways=0
WQ Output nsm derived pathways=0
WQ Create Restart=0
WQ Fixed Restart=0
WQ System Summary=0
WQ Write To DSS=0
Sorting and Armoring Iterations= 10
XS Update Threshold= 0.02
Bed Roughness Predictor= 0
Hydraulics Update Threshold= 0.02
Energy Slope Method= 1
Volume Change Method= 1
Sediment Retention Method= 0
Sediment TS Multiplier= 1
Warm Up Method= 0
XS Weighting Method= 0
Number of US Weighted Cross Sections= 1
Number of DS Weighted Cross Sections= 1
Upstream XS Weight=0
Main XS Weight=1
Downstream XS Weight=0
Number of DS XS's Weighted with US Boundary= 1
Upstream Boundary Weight= 1
Weight of XSs Associated with US Boundary= 0
Number of US XS's Weighted with DS Boundary= 1
Downstream Boundary Weight= 0.5
Weight of XSs Associated with DS Boundary= 0.5
Percentile Method= 0
Sediment Output Level= 3
Mass or Volume Output= 0
Output Increment Type= 1
Profile and TS Output Increment= 1
Transport Output Increment 1
XS Output Flag= 0
XS Output Increment= 10
Read HDF5 Sediment Hotstart= 0
Sediment Hotstart Type= 0
Write Gradation File= 0
Read Gradation Hotstart= 0
Write HDF5 File= 1
Write Binary Output= 1
Write DSS Sediment File= 0
DSS Sediment Output Type= 1
SV Curve= 0
Specific Gage Flag= 0
Subcell Erosion Methods= 0
Subcell Deposition Methods= 0
Advection Scheme= 1
Matrix Solver= 0
Implicit Weighting Factor= 1
Maximum Outer Loop Convergence Iterations= 5
Convergence Maximum Absolute= 0.001
Convergence RMSE= 0.0001
Grain Fractions Max Abs Error= 0.001
Max Subgrid Regions= 1
Max Subgrid Length Scale= 3.402823E+38
Initial Layer Thickness= 3.402823E+38
Min Layer Thickness= 3.402823E+38
Max Layer Thickness= 3.402823E+38
Number of Layers= 5

--- LIGHTRN.f01 (steady flow) ---

Flow Title=Flow
Program Version=6.20
Number of Profiles= 1
Profile Names=P100yr
River Rch & RM=LIGHTRN,Main,5396
     334
River Rch & RM=LIGHTRN,Main,3011
     530
River Rch & RM=LIGHTRN,Main,1400
     597
Boundary for River Rch & Prof#=LIGHTRN,Main            , 1
Up Type= 0
Dn Type= 3
Dn Slope=0.02249
DSS Import GetInterval= 0
DSS Import GetPeak= 0
DSS Import FillOption= 0

--- LIGHTRN.g01 (geometry) ---

Geom Title=Geometry
Program Version=6.20

River Reach=LIGHTRN         ,Main
Reach XY= 30
2230560.27993017632572.7028821312230687.74800003632695.535000011
2230835.66500002632676.7850000112230904.28985755632828.234344125
2231023.12500058632929.0393275322231093.30300002633154.562000006
     2231138.442633195.5349999962231264.59999999633269.569999993
     2231418.998633267.7570000142231497.47000003633391.368000001
2231462.29028414633523.9359838032231591.23600002633849.725000009
     2231783.581633974.7020000222231850.24800001634126.785000011
2232025.60200003634246.395999998      2232267.28634276.561000004
2232331.06300001634243.264000013     2232382.721634267.001000017
2232429.03200004634343.1139999932232565.81299999634447.395999998
2232602.40307413634584.5358031692232758.10200003 634788.88000001
2232962.42300001634947.6289999932233074.49100004 635005.03200002
2233337.21600001635069.297000021     2233610.294634976.613999993
     2233656.473635042.7259999962233920.24383292634849.251328722
2234016.13150004634844.3340124342234335.39807843634939.013107896

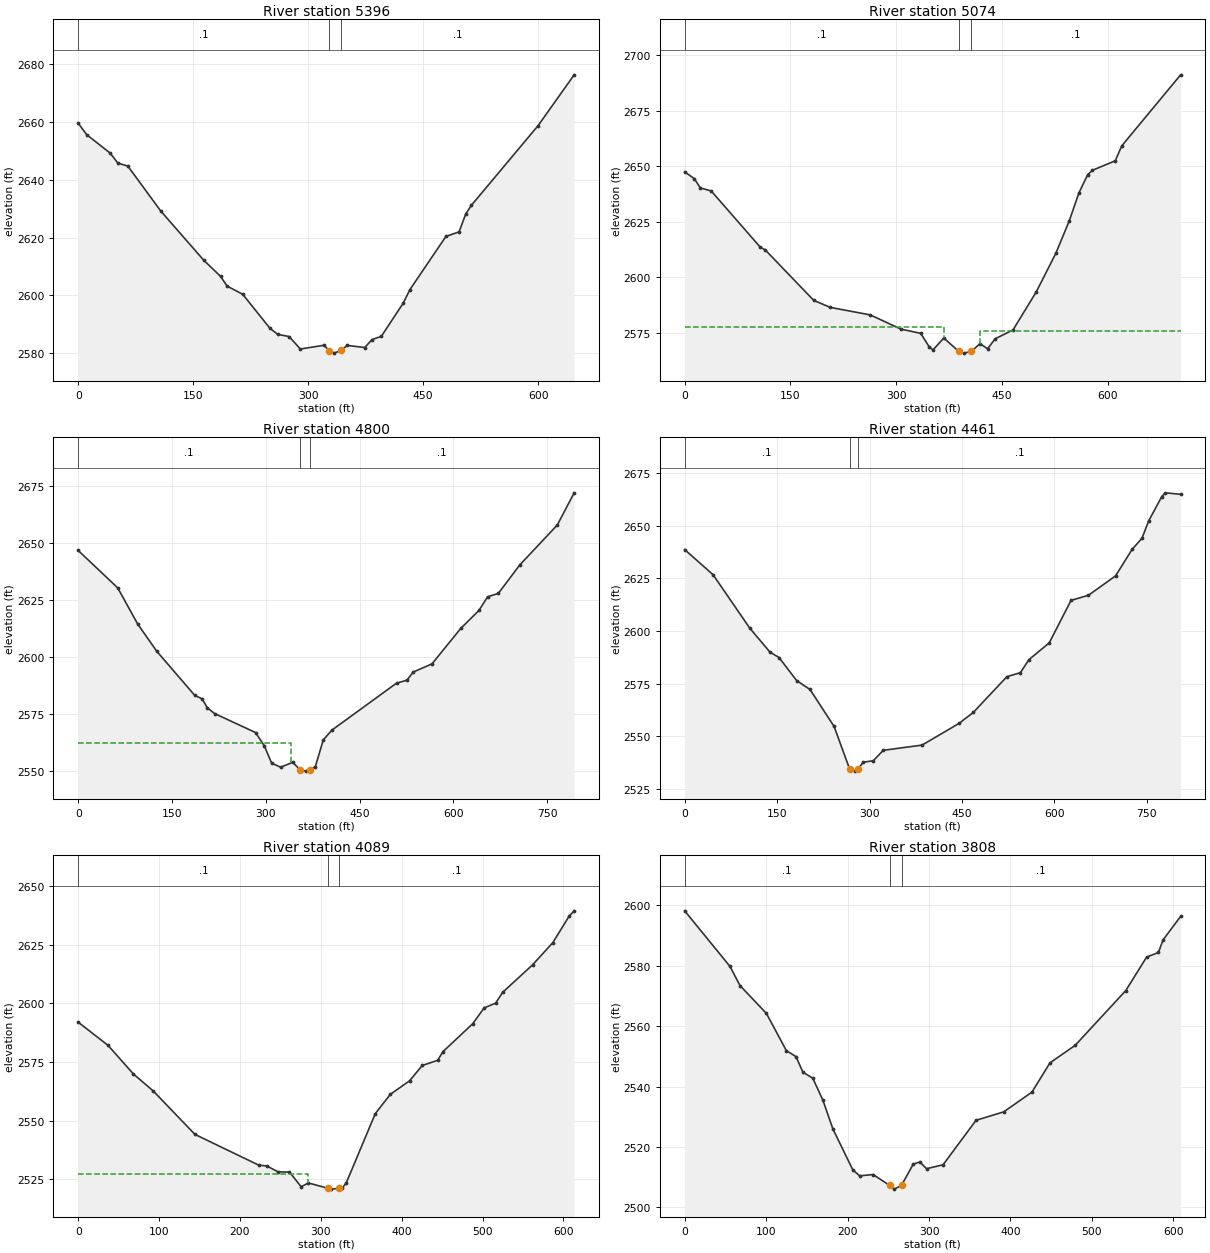
Type RM Length L Ch R = 1 ,5396    ,321.4,321.4,321.4
XS GIS Cut Line= 3
2230380.18869047632849.9059536582230542.02733841632643.929492636
2230682.18425362632285.406554843
#Sta/Elev= 30
       0 2659.61    11.1 2655.64    41.6 2649.27    51.8 2645.78    64.7 2644.76
   107.8 2629.15   163.7 2612.14   185.7 2606.53   194.2 2603.18   214.6 2600.32
   250.2 2588.51   260.4 2586.42     275  2585.7   289.8 2581.37   320.7 2582.67
  327.13 2580.85   333.6 2579.94   342.9 2580.86   350.8 2582.62   373.8 2581.88
   383.1 2584.61   395.4 2585.76   423.8  2597.2   432.6 2601.92   479.6 2620.36
   496.8 2621.98   505.4 2628.09   512.7 2631.11   599.9 2658.79   646.9 2676.38
#Mann= 3 ,0,0
       0      .1       0  327.13    .045       0   342.9      .1       0
Bank Sta=327.13,342.9
XS Rating Curve= 0 ,0
Exp/Cntr(USF)=0,0
Exp/Cntr=0.3,0.1

Type RM Length L Ch R = 1 ,5074    ,269.7,275,276.9
XS GIS Cut Line= 3
2230549.53702418632953.8074896112230765.21132685632767.949867339
2230981.99853509632409.874867339
#Sta/Elev= 30
       0 2647.46    13.7  2644.4    22.2 2640.24    37.7 2638.85   107.3 2613.57
   114.4 2612.34     183 2589.69   206.5 2586.54   263.2 2583.17   306.7 2576.78
   334.7 2574.87   347.1 2568.65   352.2 2567.48   367.5 2572.78  388.87 2566.73
   395.5 2565.99   406.52566.739   418.9 2570.28   429.5 2567.94   440.3 2572.43
   465.6 2576.42   498.4 2593.41   526.4  2610.9   545.2 2625.29   559.2 2638.11
   571.4 2646.11   577.9 2648.12   610.6 2652.44   619.9 2659.17   703.3 2691.07
#Mann= 3 ,0,0
       0      .1       0  388.87    .045       0   406.5      .1       0
#XS Ineff= 2 , 0
          367.64 2577.84  418.46         2575.79
Permanent Ineff=
       F       F
Bank Sta=388.87,406.5
XS Rating Curve= 0 ,0
Exp/Cntr(USF)=0,0
Exp/Cntr=0.3,0.1

Type RM Length L Ch R = 1 ,4800    ,338.6,338.3,336.8
XS GIS Cut Line= 3
 2230689.1325343633104.0195096882231001.84594955632860.290182405
2231240.25400646632543.628591203
#Sta/Elev= 30
       0 2646.72    63.2 2630.29    95.1 2614.41   125.6 2602.45   186.4 2583.06
     198 2581.58   206.5 2577.62   217.9 2575.12   283.5 2566.76   297.4    2561
   309.2 2553.34   323.5 2551.53     343 2553.66   354.8 2550.38   363.9 2549.81
     3702550.402   379.1 2551.76   391.8  2563.5   405.4 2567.78   508.9 2588.45
   525.5 2589.73   535.6 2593.32   565.6 2596.92   611.7 2612.51   640.7  2620.4
   654.6 2626.38   671.7 2627.88     706 2640.39     766 2657.93   792.9 2672.05
#Mann= 3 ,-1,0
       0      .1       0   354.8    .045       0     370      .1       0
#XS Ineff= 2 , 0
           340.5 2562.17
Permanent Ineff=
       F       F
Bank Sta=354.8,370
XS Rating Curve= 0 ,0
Exp/Cntr(USF)=0,0
Exp/Cntr=0.3,0.1

Type RM Length L Ch R = 1 ,4461    ,371.5,372.1,374.6
XS GIS Cut Line= 3
2230929.26959766633379.7253971042231198.26105045633083.378887416
2231468.72627684632782.620459243
#Sta/Elev= 30
       0 2638.73      46 2626.82   105.5 2601.45   138.5 2589.98   153.1 2587.45
   181.7 2576.49   203.3 2572.27   242.4 2554.72  267.552534.517   275.7 2533.46
   281.4  2534.5   289.7 2537.72     306 2538.38   322.2 2543.35   385.2 2545.83
     445 2556.11   468.3 2561.35   522.7 2578.32   544.8 2580.27   558.6 2586.47
   591.5 2594.39   626.9  2614.6   655.2 2617.04   699.1 2626.23     726 2638.83
   742.1 2644.16   752.8 2652.33   774.2 2663.96   779.8 2665.71   804.7 2665.02
#Mann= 3 ,-1,0
       0      .1       0  267.55    .045       0   281.4      .1       0
Bank Sta=267.55,281.4
XS Rating Curve= 0 ,0
Exp/Cntr(USF)=0,0
Exp/Cntr=0.3,0.1

Type RM Length L Ch R = 1 ,4089    ,278.3,281.4,283.6
XS GIS Cut Line= 3
2231164.78612511633460.5324920672231473.15091394 633273.63242972
 2231662.8073847633106.690215097
#Sta/Elev= 30
       0 2591.92    36.9 2582.02    68.2 2569.85    92.8 2562.58   144.3 2544.09
   223.3 2530.96   233.2 2530.63   247.2  2528.1   261.2 2528.03   275.7 2521.76
   284.6 2523.39  309.462521.053   312.7 2520.75   322.3 2521.05   326.7 2521.29
   331.4  2523.4   367.3 2552.91   385.9 2561.14   409.7 2566.92   425.4 2573.46
   444.5 2575.66   450.9 2579.33   487.8 2591.25   501.9 2598.01   516.1 2600.01
   524.7  2604.6   561.8 2616.36   586.9 2625.85   606.8 2637.01   613.2 2639.38
#Mann= 3 ,-1,0
       0      .1       0  309.46    .045       0   322.3      .1       0
#XS Ineff= 2 , 0
          284.61 2527.32
Permanent Ineff=
       F       F
Bank Sta=309.46,322.3
XS Rating Curve= 0 ,0
Exp/Cntr=0.3,0.1

Type RM Length L Ch R = 1 ,3808    ,189.4,188.2,186
XS GIS Cut Line= 4
2231213.39233154633593.5440220922231370.20930375633564.698913371
2231529.98971029633527.5859262672231735.77126382633329.645772066
#Sta/Elev= 30
       0  2598.2    55.7 2579.76    67.9 2573.46   100.4 2564.21   124.8 2551.92
   136.7 2549.92   145.2 2544.76   157.3 2542.76   169.7 2535.49     182 2525.96
   206.6 2512.33   214.9 2510.42   231.3 2510.86   251.8 2507.25   257.3 2506.02
  266.26 2507.27   280.7 2514.32   288.8    2515     297 2512.78   317.3 2514.09
   357.8 2528.82   391.8 2531.61   426.4 2538.15   448.6 2547.85   479.5 2553.64
   541.7  2571.8   567.2 2582.85   581.8 2584.41   587.4 2588.55     609 2596.36
#Mann= 3 ,-1,0
       0      .1       0   251.8    .045       0  266.26      .1       0
Bank Sta=251.8,266.26
XS Rating Curve= 0 ,0
Exp/Cntr(USF)=0,0
Exp/Cntr=0.3,0.1

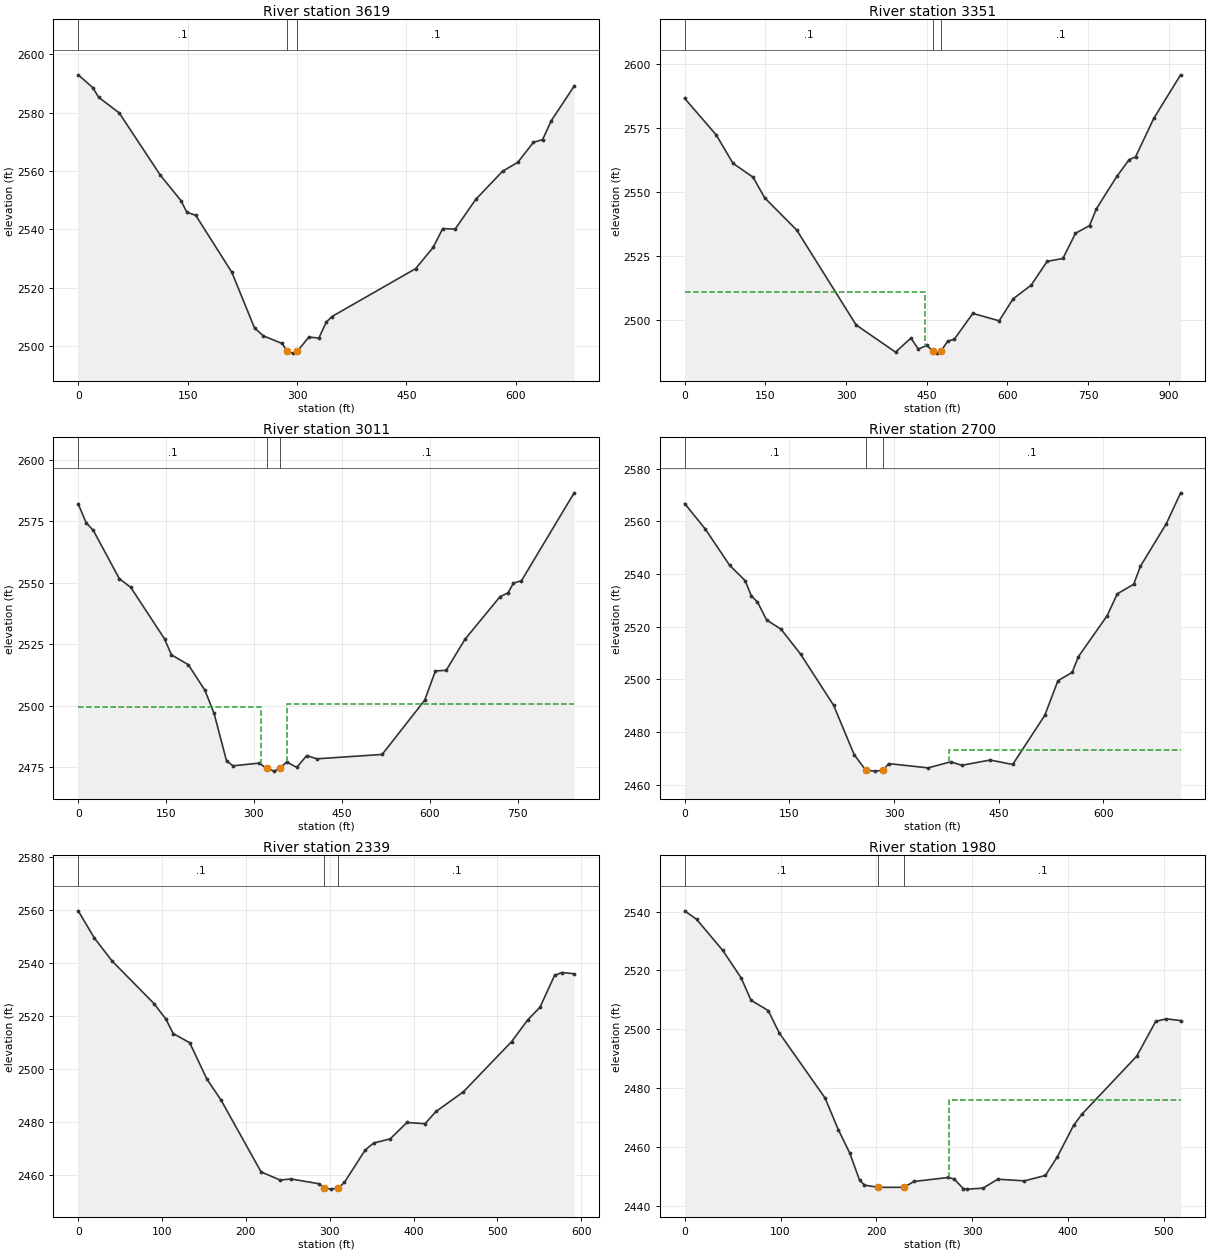
Type RM Length L Ch R = 1 ,3619    ,272.7,268.5,265.3
XS GIS Cut Line= 4
2231256.32174709633760.1807800032231506.94834186633729.168951441
2231604.66590525633680.5462273442231841.75420403633468.233837379
#Sta/Elev= 30
       0 2592.95      20 2588.56    28.1 2585.24    56.2 2579.91   112.7 2558.55
   140.9 2549.85     149 2545.87   161.1 2544.84   210.6 2525.32   241.7 2506.25
   253.9 2503.53   279.5 2500.94   286.3  2498.3   294.1 2497.63  300.522498.278
   316.1 2503.14   329.9 2502.79     340  2508.2   347.7 2510.14   462.7 2526.59
   486.7 2533.86   499.7  2540.3   516.7 2540.09     545 2550.28   581.8 2559.94
   602.6 2562.97   624.1 2569.84   636.6 2570.74   648.5 2577.22   679.9 2589.09
#Mann= 3 ,-1,0
       0      .1       0   286.3    .045       0  300.52      .1       0
Bank Sta=286.3,300.52
XS Rating Curve= 0 ,0
Exp/Cntr(USF)=0,0
Exp/Cntr=0.3,0.1

Type RM Length L Ch R = 1 ,3351    ,340.5,339.5,332.7
XS GIS Cut Line= 3
2231258.92020178633910.3272780612231643.32469209633978.265219933
 2231943.9832833633540.032824053
#Sta/Elev= 30
       0  2586.5    58.8 2572.19    89.8 2561.15   127.2  2555.7   148.5 2547.73
   208.4 2535.05   318.7 2498.03   391.9 2487.43   420.5  2492.9   434.3 2488.63
   449.9 2490.04   461.42487.883   469.3 2487.04   476.7 2487.87   488.7 2491.68
   501.1 2492.46   535.6 2502.55   584.5 2499.65   610.4 2508.23   643.9 2513.55
   673.7 2522.86     703    2524   726.4 2533.83   752.5 2536.82   765.2 2543.39
   803.2 2556.02   826.2  2562.6     838 2563.66   871.9 2578.69   921.8  2595.7
#Mann= 3 ,-1,0
       0      .1       0   461.4    .045       0   476.7      .1       0
#XS Ineff= 2 , 0
          446.93 2510.83
Permanent Ineff=
       F       F
Bank Sta=461.4,476.7
XS Rating Curve= 0 ,0
Exp/Cntr=0.3,0.1

Type RM Length L Ch R = 1 ,3011    ,314.5,311.5,308.7
XS GIS Cut Line= 4
2231825.63415779634478.3627114692231867.04379944634237.011138419
2231965.57661112633975.9158689162232123.82692494633694.900830512
#Sta/Elev= 30
       0 2582.16    13.6 2574.44    25.6 2571.43    70.2 2551.69    89.8 2548.12
   147.3 2527.18   159.1 2520.67   187.9 2516.64   216.3  2506.2   231.9 2496.79
   253.2 2477.43   264.2 2475.43   308.8 2476.53   321.7 2474.36   334.5 2473.27
  343.75 2474.37   355.9 2477.01     373 2474.79   390.1 2479.63   407.2 2478.28
   518.8 2480.07   591.4 2502.18   609.7 2514.09   628.1 2514.36   660.2    2527
   719.9 2544.34   733.7 2545.92   742.8 2549.85   756.6 2550.87   846.5 2586.67
#Mann= 3 ,-1,0
       0      .1       0   321.7    .045       0  343.75      .1       0
#XS Ineff= 2 , 0
          311.91 2499.59  355.96         2500.55
Permanent Ineff=
       F       F
Bank Sta=321.7,343.75
XS Rating Curve= 0 ,0
Exp/Cntr=0.3,0.1

Type RM Length L Ch R = 1 ,2700    ,354.9,360.9,364.6
XS GIS Cut Line= 4
2232075.57786858634523.8067474252232170.77126446634318.612094084
2232206.73321402634058.4168120122232316.73447148633865.914611455
#Sta/Elev= 30
       0 2566.74    29.4 2557.11    64.6 2543.25    86.7 2537.47    95.5 2531.68
   104.3 2529.37   117.5 2522.51     138 2519.07     166 2509.61   213.3 2490.22
   242.9  2471.4  259.482465.536   272.1 2465.17  284.522465.503   292.3 2468.03
   348.8  2466.4   381.1 2468.71   397.2 2467.39   437.6 2469.38     470  2467.7
     516 2486.37   534.8 2499.47   555.3 2502.69   564.1 2508.61   605.5 2524.24
   619.8 2532.46   643.3 2536.09     653 2542.94   690.2 2559.13   710.6 2570.81
#Mann= 3 ,-1,0
       0      .1       0  259.48    .045       0  284.52      .1       0
#XS Ineff= 2 , 0
                          378.93         2473.12
Permanent Ineff=
       F       F
Bank Sta=259.48,284.52
XS Rating Curve= 0 ,0
Exp/Cntr(USF)=0,0
Exp/Cntr=0.3,0.1

Type RM Length L Ch R = 1 ,2339    ,356.7,358.9,359.8
XS GIS Cut Line= 2
2232289.23415711634612.6539169132232640.39201747634136.686937514
#Sta/Elev= 30
       0  2559.8    19.2 2549.55    40.4 2540.85    90.4 2524.76   104.7 2518.85
   113.3 2513.45     133 2509.96   153.4 2496.28   170.5 2488.23   218.1 2461.17
   240.8 2458.12   254.2 2458.49   287.7 2456.67   292.6 2455.13   301.4 2454.67
  310.262455.118   317.5 2457.22   342.3 2469.46   352.3 2472.07   372.2 2473.66
     392 2479.85   413.6 2479.38   426.8 2484.01   459.4 2491.43     517 2510.43
   536.2 2518.64   550.7 2523.34   568.1 2535.38   576.7 2536.49   591.5 2536.02
#Mann= 3 ,-1,0
       0      .1       0   292.6    .045       0  310.26      .1       0
Bank Sta=292.6,310.26
XS Rating Curve= 0 ,0
Exp/Cntr(USF)=0,0
Exp/Cntr=0.3,0.1

Type RM Length L Ch R = 1 ,1980    ,312.2,310.2,306.3
XS GIS Cut Line= 2
2232494.42881045634786.1174382942232896.35648195634460.344483505
#Sta/Elev= 30
       0 2540.28    12.5 2537.37    39.6 2526.87    58.9 2517.47    69.2 2509.85
    87.2 2506.34    98.6 2498.76   146.4 2476.62   160.3  2465.8   172.2 2457.86
   182.5 2448.58   187.6 2446.95  201.84 2446.19   228.8 2446.19   239.1 2448.18
   274.9 2449.54     281 2449.06   290.6 2445.79   294.8 2445.58   311.2 2445.91
   326.6 2448.95   354.5  2448.4   376.3 2450.23   388.7 2456.53   405.7 2467.25
   414.4 2471.07   471.6 2490.83   491.4 2502.65   502.4 2503.53   517.4 2502.94
#Mann= 3 ,0,0
       0      .1       0  201.84    .045       0   228.8      .1       0
#XS Ineff= 2 , 0
                          275.96         2475.79
Permanent Ineff=
       F       F
Bank Sta=201.84,228.8
XS Rating Curve= 0 ,0
Exp/Cntr(USF)=0,0
Exp/Cntr=0.3,0.1

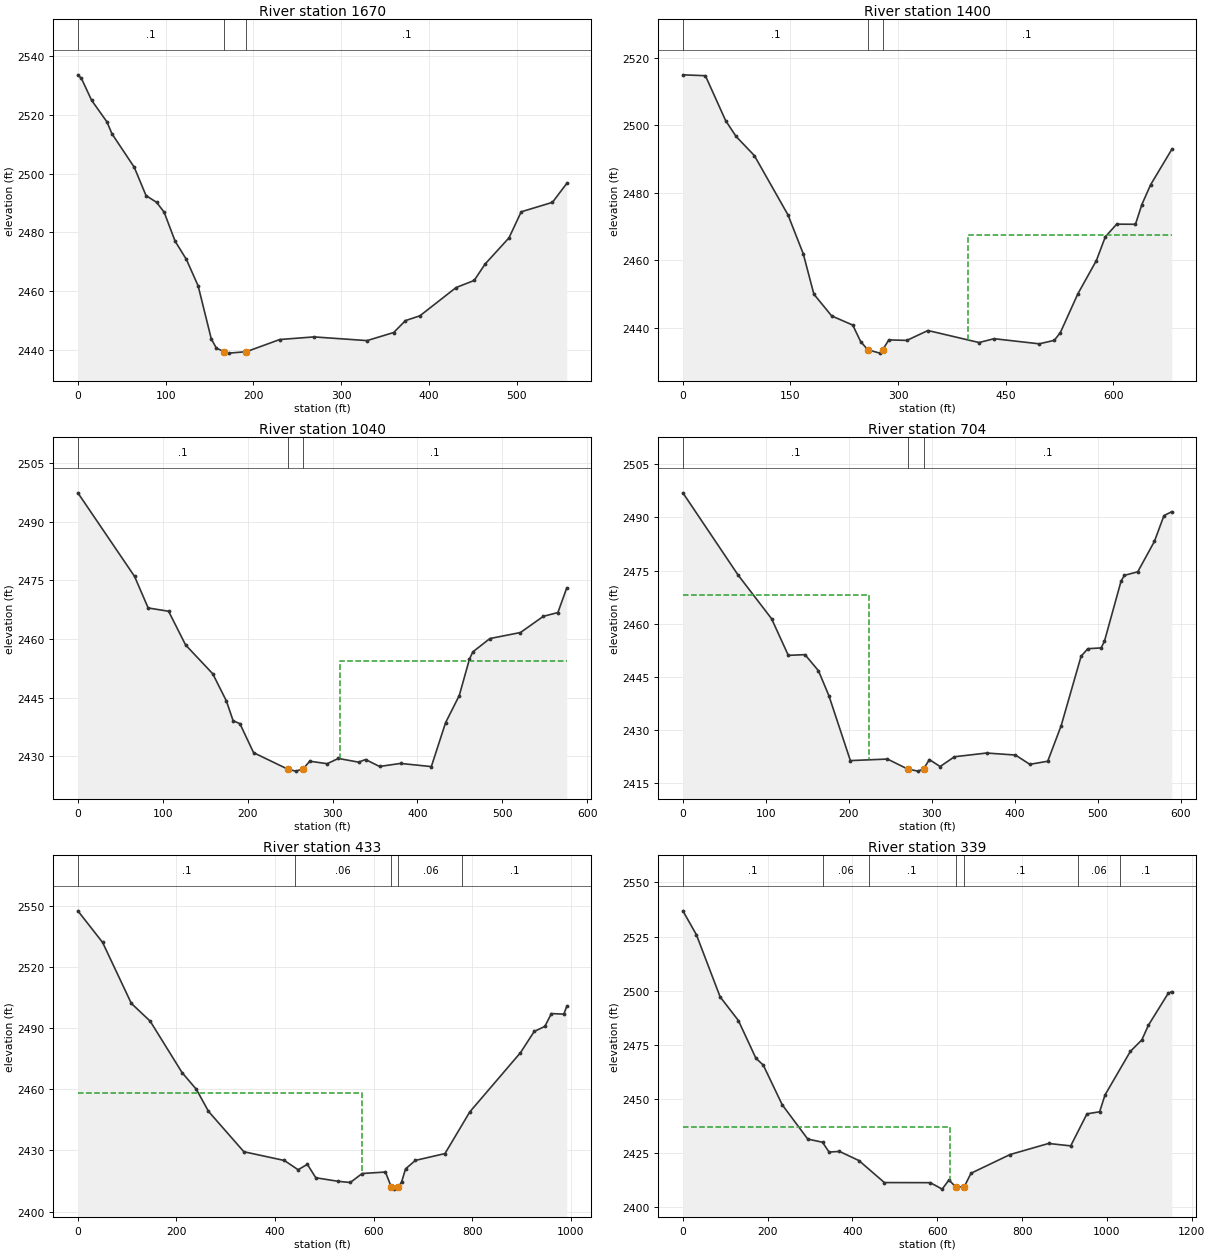
Type RM Length L Ch R = 1 ,1670    ,273.3,270.1,265.4
XS GIS Cut Line= 4
2232744.04704854 635004.004544422232843.47126201 634908.81114854
2232983.08824264634729.0014007672233029.62723618634542.845426601
#Sta/Elev= 30
       0 2533.64     4.1 2532.39    15.7 2524.95    33.2 2517.58    38.8 2513.58
    64.3 2502.12    77.7 2492.48    89.8 2490.16    98.3 2486.84   110.9  2476.9
   123.7 2470.72   137.1 2461.69   152.1  2443.6   157.8 2440.52   166.4 2439.25
   172.1 2438.77   192.1 2439.26   230.1 2443.41   269.2  2444.3   329.6 2443.04
     360  2445.8   373.4 2449.86   389.9  2451.5   431.1 2461.13   451.7 2463.54
   464.1 2469.12   491.4 2478.07   505.3 2486.94   540.9 2490.17   557.2 2496.61
#Mann= 3 ,-1,0
       0      .1       0   166.4    .045       0   192.1      .1       0
Bank Sta=166.4,192.1
XS Rating Curve= 0 ,0
Exp/Cntr(USF)=0,0
Exp/Cntr=0.3,0.1

Type RM Length L Ch R = 1 ,1400    ,364.7,360.2,354.4
XS GIS Cut Line= 3
2232902.70270834635156.3139778282233074.05082092635092.851713908
2233224.24484553634616.884734508
#Sta/Elev= 30
       0 2514.97    31.4 2514.71    59.6 2501.41    74.1 2496.72    99.7 2491.02
   146.6 2473.42   167.9 2461.89   182.7 2449.92   207.5 2443.47   236.9 2440.75
   247.9 2435.87   257.9 2433.42   274.7 2432.43  278.412433.356   287.2 2436.35
   312.4 2436.21   341.8 2439.14   413.1 2435.57     434 2436.71     497 2435.19
   517.9 2436.22   526.3 2438.46   550.8    2450   576.7  2459.9   589.2 2466.95
     605 2470.68   631.2 2470.65   640.1  2476.5   652.2 2482.32   681.8 2492.85
#Mann= 3 ,-1,0
       0      .1       0   257.9    .045       0  278.41      .1       0
#XS Ineff= 2 , 0
                          398.27         2467.41
Permanent Ineff=
       F       F
Bank Sta=257.9,278.41
XS Rating Curve= 0 ,0
Exp/Cntr(USF)=0,0
Exp/Cntr=0.3,0.1

Type RM Length L Ch R = 1 ,1040    ,334.6,336,329.4
XS GIS Cut Line= 4
2233471.74767482635295.9309584512233463.28603963635101.313349097
 2233410.4008197634881.3108341742233420.97786368634726.885991969
#Sta/Elev= 30
       0 2497.42    66.8 2476.04    82.8 2467.97   106.9 2467.12   126.9 2458.51
   158.9 2451.13   174.9 2444.21   182.9 2439.12   190.9 2438.36     207 2430.94
   247.2 2426.73   256.6 2426.22  265.252426.757   273.1 2428.76   293.7 2428.12
   306.9 2429.46   330.7 2428.52   338.9 2429.19   355.4 2427.41   380.1 2428.19
   416.4 2427.38   433.2 2438.62   449.3 2445.56   461.3 2454.87   465.3 2456.73
   485.4 2460.14   521.4 2461.68   548.4 2465.83   565.5 2466.79   575.9 2473.08
#Mann= 3 ,-1,0
       0      .1       0   247.2    .045       0  265.25      .1       0
#XS Ineff= 2 , 0
                          309.23          2454.4
Permanent Ineff=
       F       F
Bank Sta=247.2,265.25
XS Rating Curve= 0 ,0
Exp/Cntr(USF)=0,0
Exp/Cntr=0.3,0.1

Type RM Length L Ch R = 1 ,704     ,267,270.2,270.7
BEGIN DESCRIPTION:
Structure XS 4
END DESCRIPTION:
XS GIS Cut Line= 4
2233734.05836569635283.2385056682233755.21245366635116.121210678
2233651.55742259634864.3875637962233638.86496981634716.308947983
#Sta/Elev= 30
       0 2496.95    66.6 2473.73   106.9 2461.42   127.1 2451.07   147.2 2451.27
   163.4 2446.74     176  2439.7   201.9 2421.36   246.6  2421.8     271 2418.98
   283.3 2418.39  290.132419.002   297.1 2421.65   310.1 2419.69   327.4 2422.45
   366.1  2423.5   400.9 2422.93   418.2 2420.31   439.8 2421.18     456 2431.23
     480 2450.81   488.1 2452.95   504.1 2453.17   508.1    2455   528.2 2472.02
   532.2 2473.66   548.3 2474.65   568.4 2483.24   579.9 2490.51   589.3 2491.63
#Mann= 3 ,-1,0
       0      .1       0     271    .045       0  290.13      .1       0
#XS Ineff= 2 , 0
          224.84  2468.1
Permanent Ineff=
       F       F
Bank Sta=271,290.13
XS Rating Curve= 0 ,0
Exp/Cntr(USF)=0,0
Exp/Cntr=0.3,0.1

Type RM Length L Ch R = 1 ,433     ,94.4,95,95.7
BEGIN DESCRIPTION:
Structure XS 3
END DESCRIPTION:
XS GIS Cut Line= 6
2233862.73605226635449.1084992362233999.01179637635114.307597021
2233945.17446536635025.1395175372233921.62063305634939.336271241
2233916.57338327634734.0814467672233731.50755792634594.440869462
#Sta/Elev= 30
       0 2547.44    50.2 2531.95   108.5 2502.05   146.8 2493.33   211.5 2468.11
   240.5  2459.9     265 2449.14   336.8 2429.33   418.9 2425.05   446.9  2420.5
   465.6 2423.17   482.7 2416.58   527.8 2414.84   552.7 2414.25   576.8 2418.66
     624 2419.38   635.6 2412.21   640.8    2411   650.5 2412.24   656.8  2414.5
   664.8 2420.92   684.8 2425.09   744.8 2428.43   795.1 2448.85     898 2477.91
   925.8 2488.29   947.4 2490.78   960.7 2497.06   985.9  2496.8   991.8 2500.58
#Mann= 5 ,-1,0
       0      .1       0  441.47     .06       0   635.6    .045       0
   650.5     .06       0  779.95      .1       0
#XS Ineff= 2 , 0
          575.45 2458.21
Permanent Ineff=
       F       F
Bank Sta=635.6,650.5
XS Rating Curve= 0 ,0
Exp/Cntr(USF)=0,0
Exp/Cntr=0.3,0.1

Type RM Length L Ch R = 1 ,339     ,258.7,258.4,257.8
BEGIN DESCRIPTION:
Structure XS 2
END DESCRIPTION:
XS GIS Cut Line= 6
2233930.03271602 635450.790915832234084.81504267635062.152682606
2234044.43704441 634993.173602252234012.47112913 634897.27585639
2234015.83596231634586.0287864912233788.70972212634501.907956789
#Sta/Elev= 30
       0 2536.86    31.9 2525.82    87.8 2497.16   130.9 2486.22   172.2 2468.81
   189.6 2465.64   234.2 2447.34   294.5 2431.49   329.3 2430.02   344.7 2425.49
   369.3 2425.78   415.1 2421.57   475.2  2411.4   583.5 2411.35   611.5 2408.37
   627.5 2412.62   643.5 2409.38  663.242409.375   679.5  2415.7   771.5 2424.33
   862.4 2429.45   914.6 2428.34     953 2443.13   982.8 2444.08   995.6 2451.88
  1055.3 2471.97  1082.3 2477.25    1098 2484.09  1144.5 2498.75  1152.9 2499.56
#Mann= 7 ,-1,0
       0      .1       0     330     .06       0  438.33      .1       0
   643.5    .045       0  663.24      .1       0  930.67     .06       0
 1030.67      .1       0
#XS Ineff= 2 , 0
          629.03 2436.93
Permanent Ineff=
       F       F
Bank Sta=643.5,663.24
XS Rating Curve= 0 ,0
Exp/Cntr(USF)=0,0
Exp/Cntr=0.3,0.1

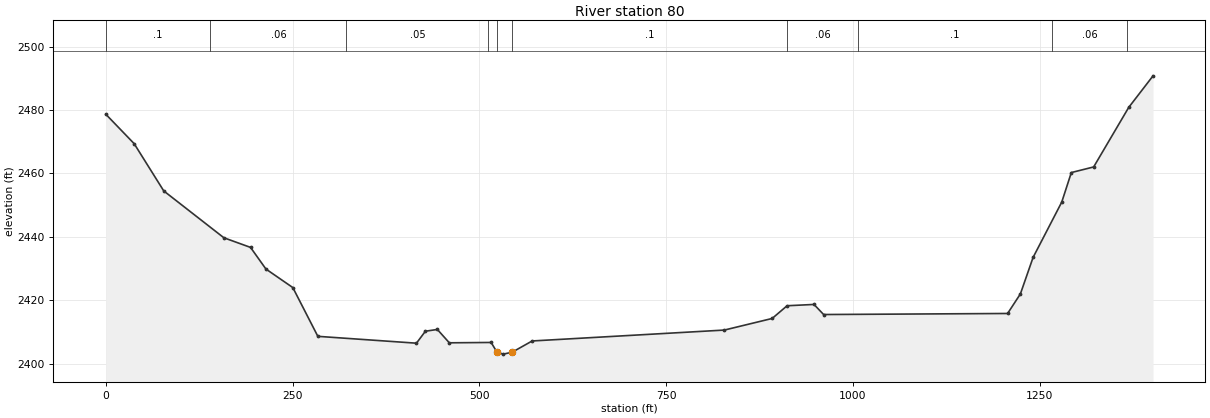
Type RM Length L Ch R = 1 ,80      ,,,
BEGIN DESCRIPTION:
Structure XS 1
END DESCRIPTION:
XS GIS Cut Line= 4
2234138.10144598635433.4325302782234262.91056502635202.852971369
2234243.87188585634458.2290747082233873.67534631634320.727502881
#Sta/Elev= 30
       0 2478.67      38 2469.38    77.6 2454.48   158.1  2439.7   193.8 2436.66
   214.4 2429.84   250.4 2423.99   283.9 2408.61   415.9 2406.45   427.9 2410.23
   443.9 2410.78   459.9 2406.57   515.9 2406.68  523.762403.586   532.1    2403
     544  2403.6   570.8 2407.15   828.1 2410.59   892.1 2414.25   912.1 2418.26
   948.1 2418.67     961 2415.49  1207.3 2415.82  1224.4 2421.99  1241.4  2433.5
  1279.8 2450.97  1292.6 2460.27  1322.5 2462.04  1369.4 2480.81    1402 2490.78
#Mann= 10 ,-1,0
       0      .1       0     140     .06       0  322.19     .05       0
  512.19      .1       0  523.76    .045       0     544      .1       0
  912.19     .06       0 1007.06      .1       0 1267.06     .06       0
 1367.06      .1       0
Bank Sta=523.76,544
XS Rating Curve= 0 ,0
Exp/Cntr(USF)=0,0
Exp/Cntr=0.3,0.1
LCMann Table=0

Chan Stop Cuts=-1
Use User Specified Reach Order=0
Composite Channel Slope=5